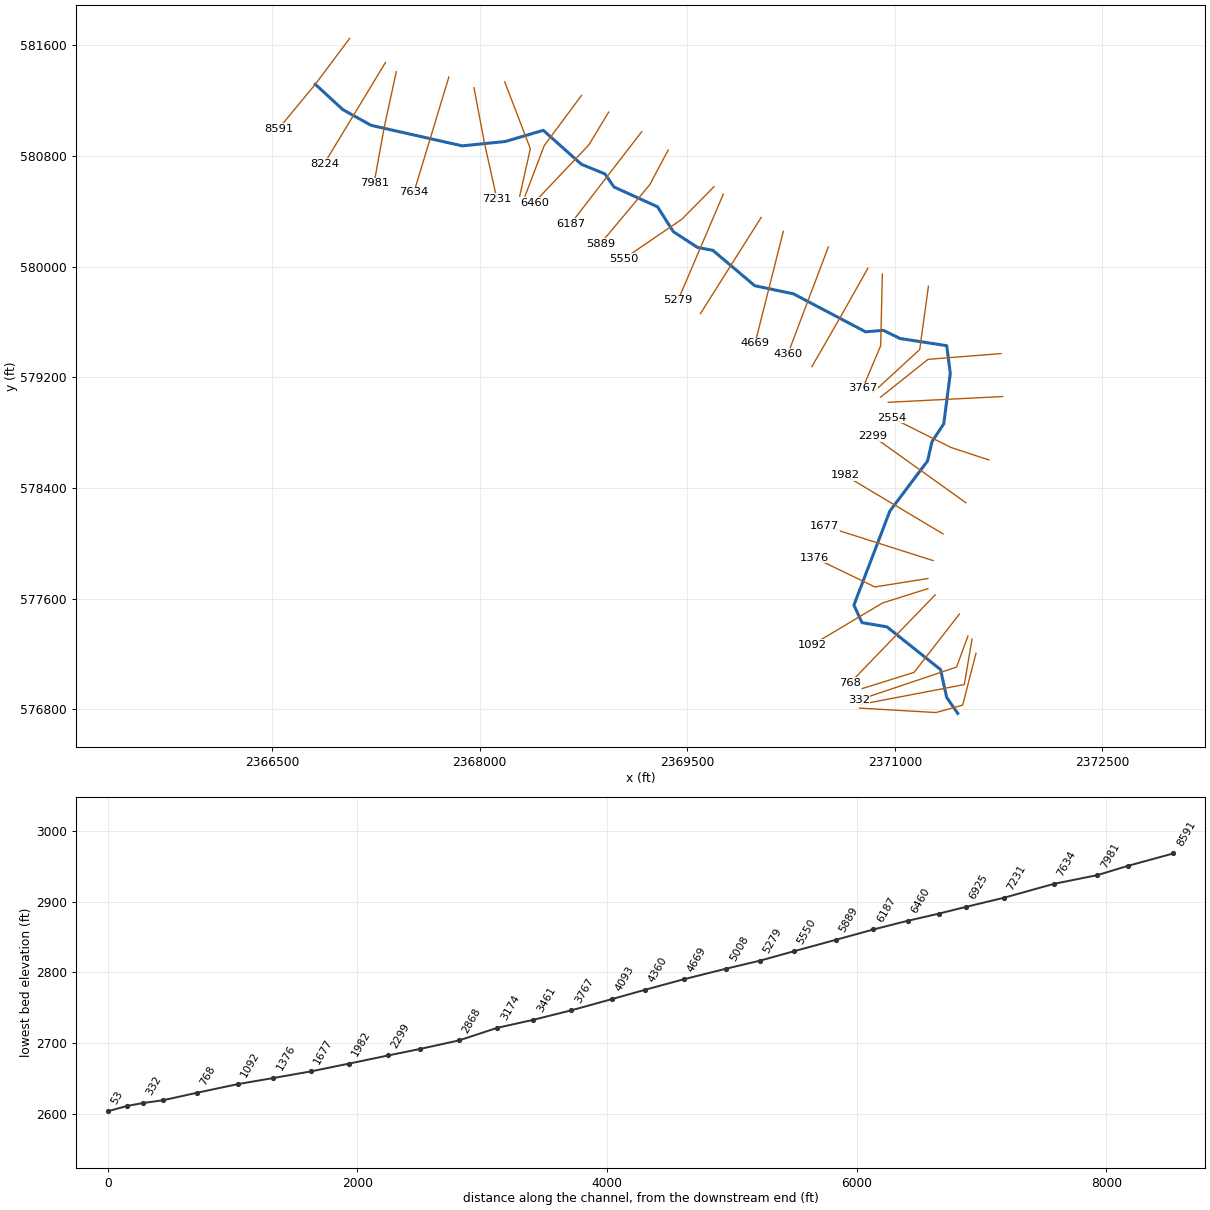
--- VANCERN.prj (project) ---

Proj Title=VANCERN
Current Plan=p01
Default Exp/Contr=0,0
English Units
Geom File=g01
Flow File=f01
Plan File=p01
BEGIN DESCRIPTION:
Stream Name: Vance Run
Flood Zone: Approximate
Pendleton County, West Virginia
HEC-RAS Version: 5.0.7
Hydrology Method:
Regression equation
END DESCRIPTION:
DSS File=dss
DSS Export Rating Curves= 0
DSS Export Rating Curve Sorted= 0
DSS Export Volume Flow Curves= 0
DXF OffsetX= 0
DXF OffsetY= 0
DXF ScaleX= 0
DXF ScaleY= 0

--- VANCERN.p01 (plan) ---

Plan Title=Floodplain
Program Version=5.07
Short Identifier=Floodplain
Geom File=g01
Flow File=f01
Subcritical Flow
K Sum by GR= 0
Std Step Tol= 0.01
Critical Tol= 0.01
Num of Std Step Trials= 20
Max Error Tol= 0.3
Flow Tol Ratio= 0.001
Split Flow NTrial= 30
Split Flow Tol= 0.02
Split Flow Ratio= 0.02
Log Output Level= 0
Friction Slope Method= 1
Unsteady Friction Slope Method= 2
Unsteady Bridges Friction Slope Method= 1
Parabolic Critical Depth
Global Vel Dist= 0 , 0 , 0
Global Log Level= 0
CheckData=True
Encroach Param=-1 ,0,0, 0
Computation Interval=0.1SEC
Output Interval=1MIN
Instantaneous Interval=Max Profile
Mapping Interval=1HOUR
Computation Time Step Use Courant=        0
Computation Time Step Use Time Series=    0
Computation Time Step Count To Double=0
Computation Time Step Max Doubling=0
Computation Time Step Max Halving=0
Computation Time Step Residence Courant=0
Run HTab= 0
Run UNet= 0
Run Sediment= 0
Run PostProcess= 0
Run WQNet= 0
Run RASMapper= 0
UNET Theta= 0
UNET Theta Warmup= 0
UNET ZTol= 0
UNET ZSATol= 0
UNET MxIter= 0
UNET Max Iter WO Improvement= 0
UNET MaxInSteps= 0
UNET DtIC= 0
UNET DtMin= 0
UNET MaxCRTS= 0
UNET WFStab= 0
UNET SFStab= 0
UNET WFX= 1
UNET SFX= 1
UNET 1D Methodology=Finite Difference
UNET DSS MLevel= 1
UNET Pardiso=0
UNET DZMax Abort= 0
UNET Use Existing IB Tables= 0
UNET Froude Reduction=False
UNET Froude Limit= 0
UNET Froude Power= 0
UNET D1 Cores= 0
UNET D2 Coriolis=0
UNET D2 Cores= 0
UNET D2 Theta= 1
UNET D2 Theta Warmup= 1
UNET D2 Z Tol= 0.01
UNET D2 Volume Tol= 0.01
UNET D2 Max Iterations= 20
UNET D2 Equation= 0
UNET D2 RampUpFraction=0.1
UNET D2 TimeSlices= 1
UNET D2 BCVolumeCheck=0
UNET D1D2 MaxIter= 0
UNET D1D2 ZTol=0.01
UNET D1D2 QTol=0.1
UNET D1D2 MinQTol=1
DSS File=dss
Write IC File= 0
Write IC File at Fixed DateTime=0
Write IC File at Sim End=0
Echo Input=False
Echo Parameters=False
Echo Output=False
Write Detailed= 0
HDF Write Warmup=0
HDF Write Time Slices=0
HDF Flush=0
HDF Face Node Velocities=0
HDF Compression= 1
HDF Chunk Size= 1
HDF Spatial Parts= 1
HDF Use Max Rows=0
HDF Fixed Rows= 1
Calibration Method= 0
Calibration Iterations= 20
Calibration Max Change=0.05
Calibration Tolerance=0.2
Calibration Maximum=1.5
Calibration Minimum=0.5
Calibration Optimization Method= 1
WQ AD Non Conservative
WQ ULTIMATE=-1
WQ Max Comp Step=1HOUR
WQ Output Interval=15MIN
WQ Output Selected Increments= 0
WQ Output face flow=0
WQ Output face velocity=0
WQ Output face area=0
WQ Output face dispersion=0
WQ Output cell volume=0
WQ Output cell surface area=0
WQ Output cell continuity=0
WQ Output cumulative cell continuity=0
WQ Output face conc=0
WQ Output face dconc_dx=0
WQ Output face courant=0
WQ Output face peclet=0
WQ Output face adv mass=0
WQ Output face disp mass=0
WQ Output cell mass=0
WQ Output cell source sink temp=0
WQ Output nsm pathways=0
WQ Output nsm derived pathways=0
WQ Output MaxMinRange=-1
WQ Daily Max Min Mean=-1
WQ Daily Range=0
WQ Daily Time=0
WQ Create Restart=0
WQ Fixed Restart=0
WQ System Summary=0
WQ Write To DSS=0
WQ Use Fixed Temperature=0
Sorting and Armoring Iterations= 10
XS Update Threshold= 0.02
Bed Roughness Predictor= 0
Hydraulics Update Threshold= 0.02
Energy Slope Method= 1
Volume Change Method= 1
Sediment Retention Method= 0
XS Weighting Method= 0
Number of US Weighted Cross Sections= 1
Number of DS Weighted Cross Sections= 1
Upstream XS Weight=0
Main XS Weight=1
Downstream XS Weight=0
Number of DS XS's Weighted with US Boundary= 1
Upstream Boundary Weight= 1
Weight of XSs Associated with US Boundary= 0
Number of US XS's Weighted with DS Boundary= 1
Downstream Boundary Weight= 0.5
Weight of XSs Associated with DS Boundary= 0.5
Percentile Method= 0
Sediment Output Level= 3
Mass or Volume Output= 0
Output Increment Type= 1
Profile and TS Output Increment= 1
XS Output Flag= 0
XS Output Increment= 10
Write Gradation File= 0
Read Gradation Hotstart= 0
Write HDF5 File= 1
Write Binary Output= 1
Write DSS Sediment File= 0
SV Curve= 0
Specific Gage Flag= 0

--- VANCERN.f01 (steady flow) ---

Flow Title=Flows
Program Version=5.07
Number of Profiles= 6
Profile Names=P100yr,P10yr,P25yr,P50yr,P500yr,P101yr
River Rch & RM=VANCERN,Main            ,8591
     800     372     527     660    1177     974
River Rch & RM=VANCERN,Main            ,7981
     899     418     592     741    1324    1094
River Rch & RM=VANCERN,Main            ,3174
    1257     581     826    1035    1857    1530
Boundary for River Rch & Prof#=VANCERN,Main            , 1
Up Type= 0
Dn Type= 3
Dn Slope=0.04951
Boundary for River Rch & Prof#=VANCERN,Main            , 2
Up Type= 0
Dn Type= 3
Dn Slope=0.04951
Boundary for River Rch & Prof#=VANCERN,Main            , 3
Up Type= 0
Dn Type= 3
Dn Slope=0.04951
Boundary for River Rch & Prof#=VANCERN,Main            , 4
Up Type= 0
Dn Type= 3
Dn Slope=0.04951
Boundary for River Rch & Prof#=VANCERN,Main            , 5
Up Type= 0
Dn Type= 3
Dn Slope=0.04951
Boundary for River Rch & Prof#=VANCERN,Main            , 6
Up Type= 0
Dn Type= 3
Dn Slope=0.04951
DSS Import GetInterval= 0
DSS Import GetPeak= 0
DSS Import FillOption= 0

--- VANCERN.g01 (geometry) ---

Geom Title=Geometry
Program Version=5.07

River Reach=VANCERN         ,Main
Reach XY= 30
2366811.59300002581317.714000002     2367010.711581134.311000019
     2367215.292581020.809000015     2367873.021580872.737000018
      2368184.34580904.0980000052368459.10800001580984.916999996
2368734.66085404580739.3173486012368904.28800002580670.185000017
2368970.61500001580574.995000005     2369284.676580432.364999995
2369399.05899999 580252.392000022369573.29700002580138.796000004
2369684.54499999580117.514000013     2369987.528579861.809000015
2370267.11500001579803.1530000122370788.64300004579528.674999997
2370917.49600002579539.349999994      2371036.75579480.531000018
2371374.58900002579428.487000003     2371400.627579229.479000017
2371353.38100001578864.270999998     2371268.502578734.927000001
2371236.29000002578595.4130000172370963.71700004578233.416999996
2370704.02300003577554.129000008     2370762.368      577427.081
2370942.88800004577396.4290000052371329.96300003577087.854000017
2371374.53400004576886.5429999982371454.24551862576771.275981158

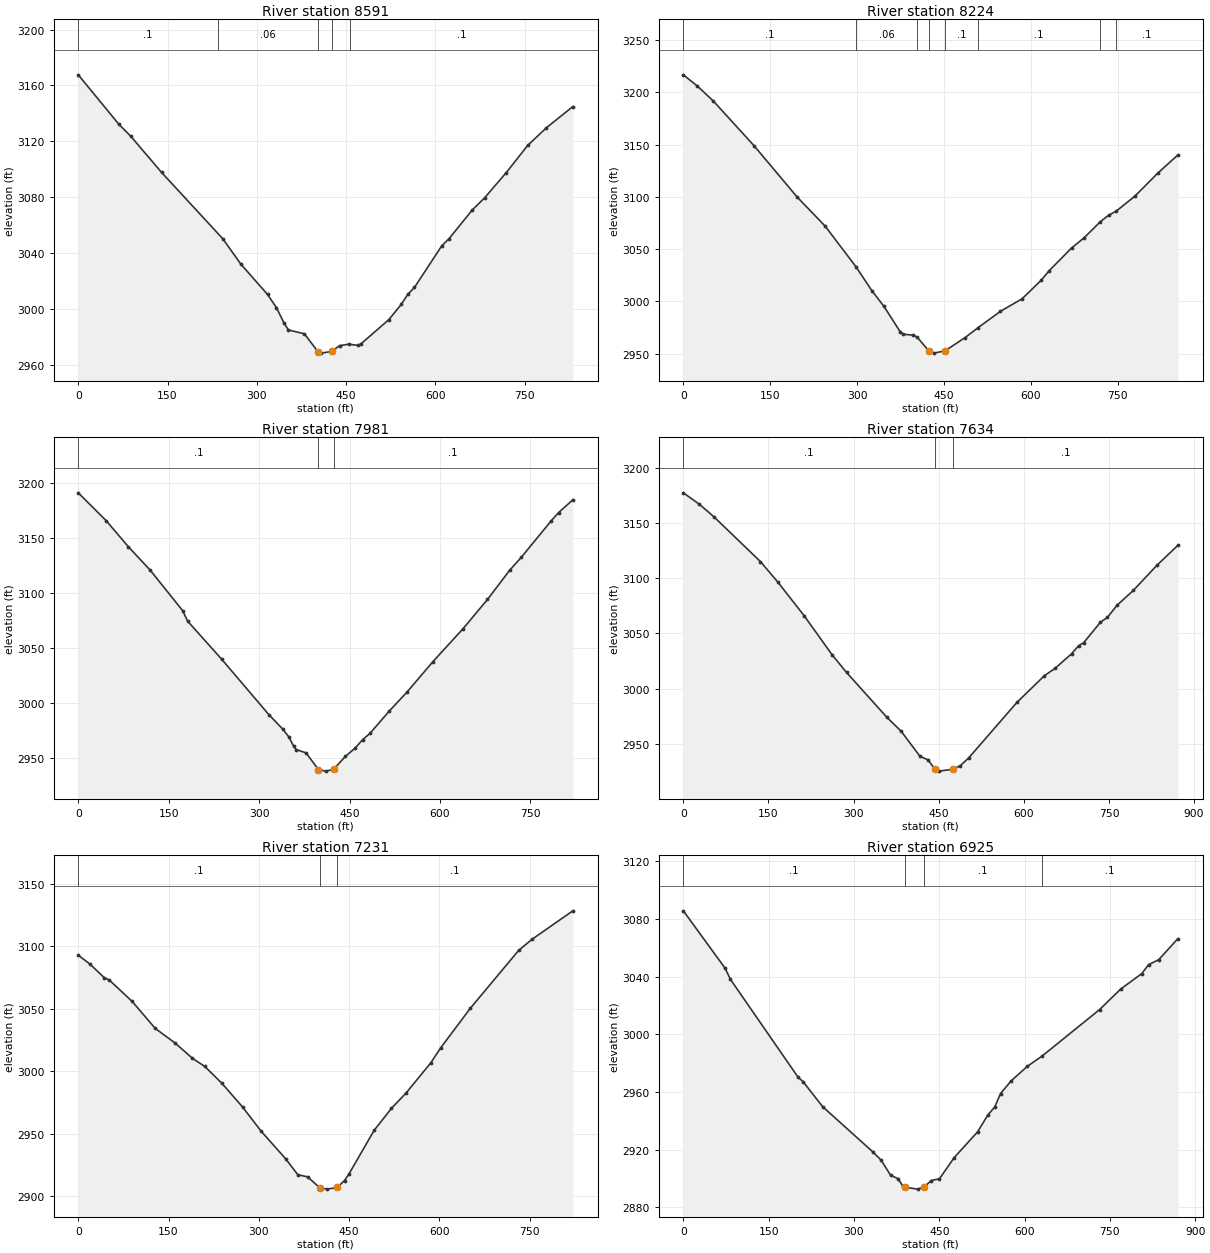
Type RM Length L Ch R = 1 ,8591    ,366.8,366.8,366.8
XS GIS Cut Line= 3
2367059.87737855581649.6908245952366813.24559435581319.714999329
2366546.33959435580996.538999329
#Sta/Elev= 30
       0 3167.57    68.4 3132.09    88.4  3123.5     140 3097.72   242.9  3050.2
   273.2 3032.07   318.1 3010.33   333.1 3000.84   345.7 2989.92   353.1 2984.92
     380  2982.2     403 2969.27     408 2968.35   425.92969.548     439 2973.67
   454.5 2974.74   470.1  2973.9   475.3 2975.06     522 2992.37   542.7 3003.19
   554.1 3010.62   564.9 3015.34   610.6 3045.03   623.2 3050.35     662 3070.77
   682.8  3079.5   719.1  3097.5   755.4 3117.11   786.8 3129.72   831.1 3144.87
#Mann= 5 ,-1 , 0
       0      .1       0  234.89     .06       0     403    .045       0
   425.9     .06       0  456.89      .1       0
Bank Sta=403,425.9
XS Rating Curve= 0 ,0
Exp/Cntr=0.3,0.1

Type RM Length L Ch R = 1 ,8224    ,243.2,243.2,243.2
XS GIS Cut Line= 2
2367318.73806105581475.057280122     2366876.423      580744.891
#Sta/Elev= 30
       0 3216.63    23.6 3206.17    51.6 3191.69   121.8 3149.02   196.6 3099.72
   244.8 3072.01  297.783033.322   326.3 3009.61   346.3 2995.33   374.3 2971.08
     379 2968.67   396.2  2967.9  403.242966.114   424.6 2952.21   432.3 2950.64
   451.5  2952.8   486.4 2965.51  508.712974.977   547.4  2990.6   584.8 3002.61
   617.6 3020.25   631.5 3029.45     670 3051.05   692.3 3061.12  719.643076.178
   734.4 3082.55  747.483086.455   779.7 3100.79   818.6  3122.5   853.7 3140.07
#Mann= 8 ,-1 , 0
       0      .1       0  297.78     .06       0  403.24      .1       0
   424.6    .045       0   451.5      .1       0  508.71      .1       0
  719.64      .1       0  747.48      .1       0
Bank Sta=424.6,451.5
XS Rating Curve= 0 ,0
Exp/Cntr=0.3,0.1

Type RM Length L Ch R = 1 ,7981    ,347,347,347
XS GIS Cut Line= 3
     2367396.789      581408.163     2367309.835      581007.774
     2367236.464      580603.582
#Sta/Elev= 30
       0 3190.94    46.3  3165.6    83.2 3141.81   119.3 3120.58   173.2 3083.64
   181.4 3074.15   238.2  3039.3   316.5 2988.85   338.9 2976.06   349.2 2968.87
   357.4 2960.28   361.5 2957.25   377.9 2954.25   398.3 2939.09   410.6 2937.62
   423.5 2939.16   443.1 2951.03   459.4 2958.57   471.6  2966.2   483.8 2971.89
   516.3 2992.52   544.8 3009.21   588.6  3037.4   638.3 3067.22   678.9 3093.87
   715.5 3120.32   734.8 3132.13   784.7 3165.53   796.8 3172.88   820.5 3184.62
#Mann= 3 ,-1 , 0
       0      .1       0   398.3    .045       0   423.5      .1       0
Bank Sta=398.3,423.5
XS Rating Curve= 0 ,0
Exp/Cntr=0.3,0.1

Type RM Length L Ch R = 1 ,7634    ,403,403,403
XS GIS Cut Line= 2
2367776.79823659581370.068684446     2367523.928      580536.012
#Sta/Elev= 30
       0 3177.11    28.4 3166.71    53.5 3155.61   135.7 3114.98   166.3  3096.5
   212.7 3066.01   262.5 3030.32   287.5 3014.64   358.6 2974.06   383.7 2961.47
   417.1 2938.67   430.8 2935.59   443.6 2927.04   450.6 2925.33   475.6 2927.13
   475.6 2927.15   488.2 2930.37   503.4 2937.63   587.9 2987.57     636 3011.56
   655.4 3018.45   684.2 3031.57   696.4 3038.75   705.5 3041.57   734.8 3059.94
   747.3 3064.46   764.3 3075.44   792.9  3088.8   834.9 3111.77   871.5 3129.63
#Mann= 3 ,-1 , 0
       0      .1       0   443.6    .045       0   475.6      .1       0
Bank Sta=443.6,475.6
XS Rating Curve= 0 ,0
Exp/Cntr=0.3,0.1

Type RM Length L Ch R = 1 ,7231    ,305.5,305.5,305.5
XS GIS Cut Line= 3
     2367958.047      581293.366     2368034.877      580888.288
     2368123.929      580488.569
#Sta/Elev= 30
       0 3092.88    18.8 3086.06    43.2 3074.89    51.4 3073.09    89.6 3055.88
   127.8 3034.33   161.3  3022.4   189.8  3010.3   210.2 3003.83   238.7 2990.29
   273.1 2971.28   303.8 2952.01   344.5  2929.9   364.9 2917.09   381.2 2915.38
   401.5 2906.55   413.4 2905.56   430.1 2906.87   430.1 2906.88   442.4 2912.42
   450.2 2918.05   491.6 2952.59   520.3 2970.21   544.9 2982.66   585.8 3006.73
   602.2 3018.75   651.4 3050.37   731.7  3096.7   753.9 3105.62   821.8 3128.45
#Mann= 3 ,-1 , 0
       0      .1       0   401.5    .045       0   430.1      .1       0
Bank Sta=401.5,430.1
XS Rating Curve= 0 ,0
Exp/Cntr=0.3,0.1

Type RM Length L Ch R = 1 ,6925    ,213.3,213.3,213.3
XS GIS Cut Line= 3
     2368180.359      581335.4832368365.54619488580852.317958282
     2368288.688      580508.537
#Sta/Elev= 30
       0 3085.67    73.5  3045.8    82.8 3038.12     202 2970.11   210.5 2967.19
   244.8 2949.87   333.7 2918.27   347.6 2912.78   364.6 2902.15   377.6 2899.85
   386.2 2894.46   389.4 2893.95   411.9  2892.6   423.5 2894.17   435.9 2898.57
   450.4 2899.79   476.1  2914.4   517.4 2932.33   535.3 2943.91   547.6 2949.63
   557.8 2958.92   576.3 2967.65   604.7 2977.72  631.09 2984.98   732.1 3017.21
   768.9 3031.35     806 3042.08   818.1 3048.32   835.9 3051.76   869.7 3066.41
#Mann= 4 ,-1 , 0
       0      .1       0   389.4    .045       0   423.5      .1       0
  631.09      .1       0
Bank Sta=389.4,423.5
XS Rating Curve= 0 ,0
Exp/Cntr=0.3,0.1

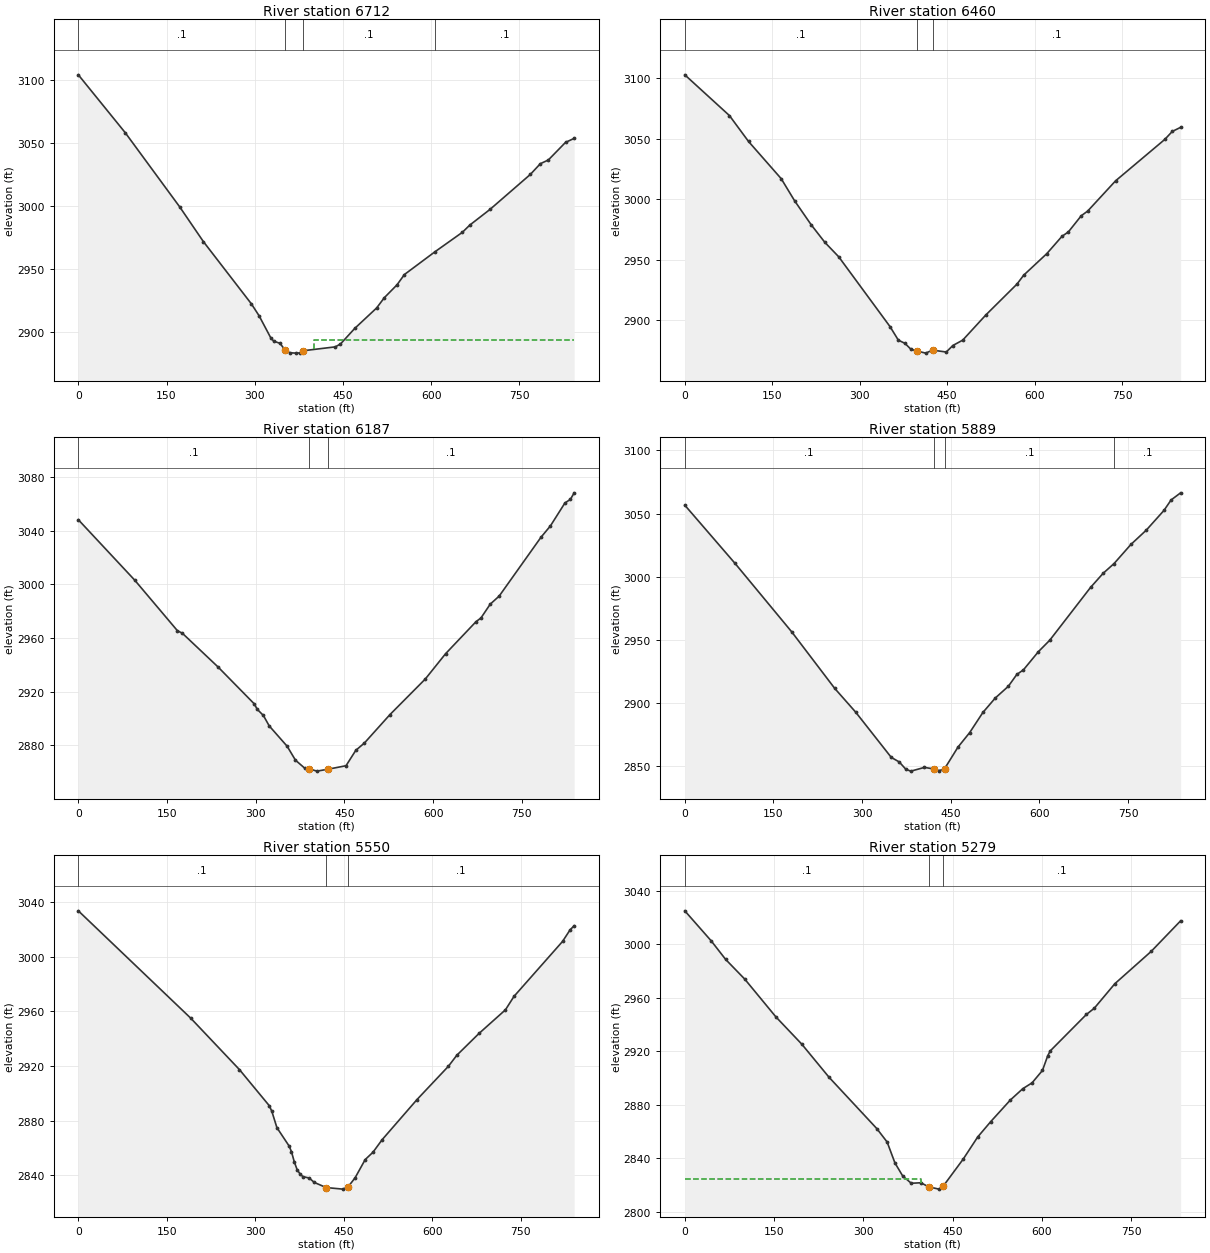
Type RM Length L Ch R = 1 ,6712    ,251.9,251.9,251.9
XS GIS Cut Line= 3
2368735.86038975581237.5207842652368466.19961949580874.908719307
      2368327.14      580509.163
#Sta/Elev= 30
       0 3104.08    79.9 3058.08   172.8 2999.01   212.6 2971.77   294.3 2922.32
   307.4 2912.86   327.3 2895.32   332.3  2892.7   342.9 2891.02   352.2 2885.31
     360 2883.49   370.5 2883.22   377.2 2883.41   382.9 2885.14     437 2888.19
   445.8 2890.47   470.1 2902.85   507.3 2919.07   520.4 2927.22   541.8 2937.34
   554.6 2945.61  606.452963.647     653 2979.07   665.9  2984.9   700.1 2997.28
   768.6    3025   785.7 3033.55   799.3  3036.5   828.5 3050.46   843.2 3053.65
#Mann= 4 ,-1 , 0
       0      .1       0   352.2    .045       0   382.9      .1       0
  606.45      .1       0
#XS Ineff= 2 , 0
                          401.58         2893.77
Permanent Ineff=
       F       F
Bank Sta=352.2,382.9
XS Rating Curve= 0 ,0
Exp/Cntr=0.3,0.1

Type RM Length L Ch R = 1 ,6460    ,272.9,272.9,272.9
XS GIS Cut Line= 3
      2368931.73      581116.3922368788.00675864580878.906074197
     2368394.045      580463.168
#Sta/Elev= 30
       0 3102.75    76.6 3069.09   109.3 3047.74   165.4 3016.98   188.2 2998.85
   216.8 2978.93   240.2 2964.45     264 2952.52   352.1 2894.79   366.2 2883.73
   377.5 2881.09   387.8  2876.2   398.8 2874.67   413.2 2873.01   424.8  2875.5
   448.4 2873.92   459.7  2879.3   476.6 2883.73   516.2 2904.48   569.7 2930.02
   581.2 2937.37   620.9 2955.18   646.8 2969.42   657.8 2973.07   679.9 2986.42
   690.9 2990.28   738.8 3015.26   823.2 3049.45   835.9 3055.98   850.3 3059.41
#Mann= 3 ,-1 , 0
       0      .1       0   398.8    .045       0   424.8      .1       0
Bank Sta=398.8,424.8
XS Rating Curve= 0 ,0
Exp/Cntr=0.3,0.1

Type RM Length L Ch R = 1 ,6187    ,298.7,298.7,298.7
XS GIS Cut Line= 2
2369169.99755453580974.476032479      2368658.26      580310.499
#Sta/Elev= 30
       0 3048.19    95.4 3003.13   167.4 2965.55     176 2963.54   235.9 2938.59
   297.4 2910.98   302.5 2906.89   312.9 2902.29   322.7 2894.55     353  2879.4
   367.1    2869   383.3 2862.82   389.9 2862.52   403.5 2860.83   421.3 2862.18
   452.6 2864.86   469.1 2876.32   483.7 2881.79   526.8 2902.93   586.7 2929.52
   620.9 2948.33   672.3 2972.19   680.8 2975.02   696.4 2985.27   711.5 2991.27
   782.2 3035.12   798.2 3043.61   822.7 3060.69     832 3063.39   838.3 3068.24
#Mann= 3 ,-1 , 0
       0      .1       0   389.9    .045       0   421.3      .1       0
Bank Sta=389.9,421.3
XS Rating Curve= 0 ,0
Exp/Cntr=0.3,0.1

Type RM Length L Ch R = 1 ,5889    ,338.3,338.3,338.3
XS GIS Cut Line= 3
      2369361.82       580842.742369228.33451828580591.491158751
     2368872.619      580166.354
#Sta/Elev= 30
       0 3056.73      85 3010.66     181 2956.42   253.6 2911.77   288.9 2893.06
   349.3 2857.15   362.7 2853.58   374.3  2847.6   382.6 2846.29   405.4 2849.24
   420.9 2848.04   430.4 2846.64   439.4 2848.14   462.1 2865.26     482 2876.81
   504.3 2892.71   525.2 2904.11   547.3  2913.4   561.7 2922.78   572.9 2926.44
   598.2 2940.81   617.4 2949.87   686.4 2991.64   707.7 3002.81  726.263010.563
   754.7 3025.64   780.8 3037.01   810.6 3052.57   822.7 3060.86   838.8  3066.5
#Mann= 4 ,-1 , 0
       0      .1       0   420.9    .045       0   439.4      .1       0
  726.26      .1       0
Bank Sta=420.9,439.4
XS Rating Curve= 0 ,0
Exp/Cntr=0.3,0.1

Type RM Length L Ch R = 1 ,5550    ,271.1,271.1,271.1
XS GIS Cut Line= 3
     2369692.779      580576.9062369459.74977361 580341.65174606
     2369038.455      580055.026
#Sta/Elev= 30
       0 3033.39   190.5 2954.99   273.1 2917.41   323.8 2890.98   328.1 2886.89
   336.7 2874.96   357.4 2861.53   361.4 2857.38   366.2 2849.92     371 2844.23
   375.9 2841.16   380.7 2839.18   391.4 2838.18     400 2834.95   420.2 2831.19
   448.5 2830.04   456.9 2831.44   469.2 2838.26   486.4 2851.64   499.6 2857.01
   515.2  2866.2   574.2 2895.47   627.5 2919.82   641.8 2927.88   679.3 2943.77
   724.2 2961.06   738.7 2970.88     821 3011.02   833.8  3019.5   840.7  3022.5
#Mann= 3 ,-1 , 0
       0      .1       0   420.2    .045       0   456.9      .1       0
Bank Sta=420.2,456.9
XS Rating Curve= 0 ,0
Exp/Cntr=0.3,0.1

Type RM Length L Ch R = 1 ,5279    ,271.2,271.2,271.2
XS GIS Cut Line= 2
      2369760.24      580523.569     2369432.939      579757.301
#Sta/Elev= 30
       0 3025.13    44.3 3002.68    68.7 2988.72   100.8 2973.98     153 2945.76
   196.5 2925.35   242.4 2900.52   322.6 2862.12     340 2852.05   353.1 2836.41
   366.1 2826.66   380.6 2821.15   396.6 2821.54   409.6 2818.53     427 2816.77
   434.4 2819.09     468 2839.35   492.2 2855.81     514 2867.26   547.2 2883.55
   567.9 2891.94   583.6 2896.36     601 2905.62   609.7 2916.39     614  2920.2
   674.9 2947.56     688 2952.15   722.8 2970.62   783.7 2994.74   833.2 3017.65
#Mann= 3 ,-1 , 0
       0      .1       0   409.6    .045       0   434.4      .1       0
#XS Ineff= 2 , 0
          396.46 2824.68
Permanent Ineff=
       F       F
Bank Sta=409.6,434.4
XS Rating Curve= 0 ,0
Exp/Cntr=0.3,0.1

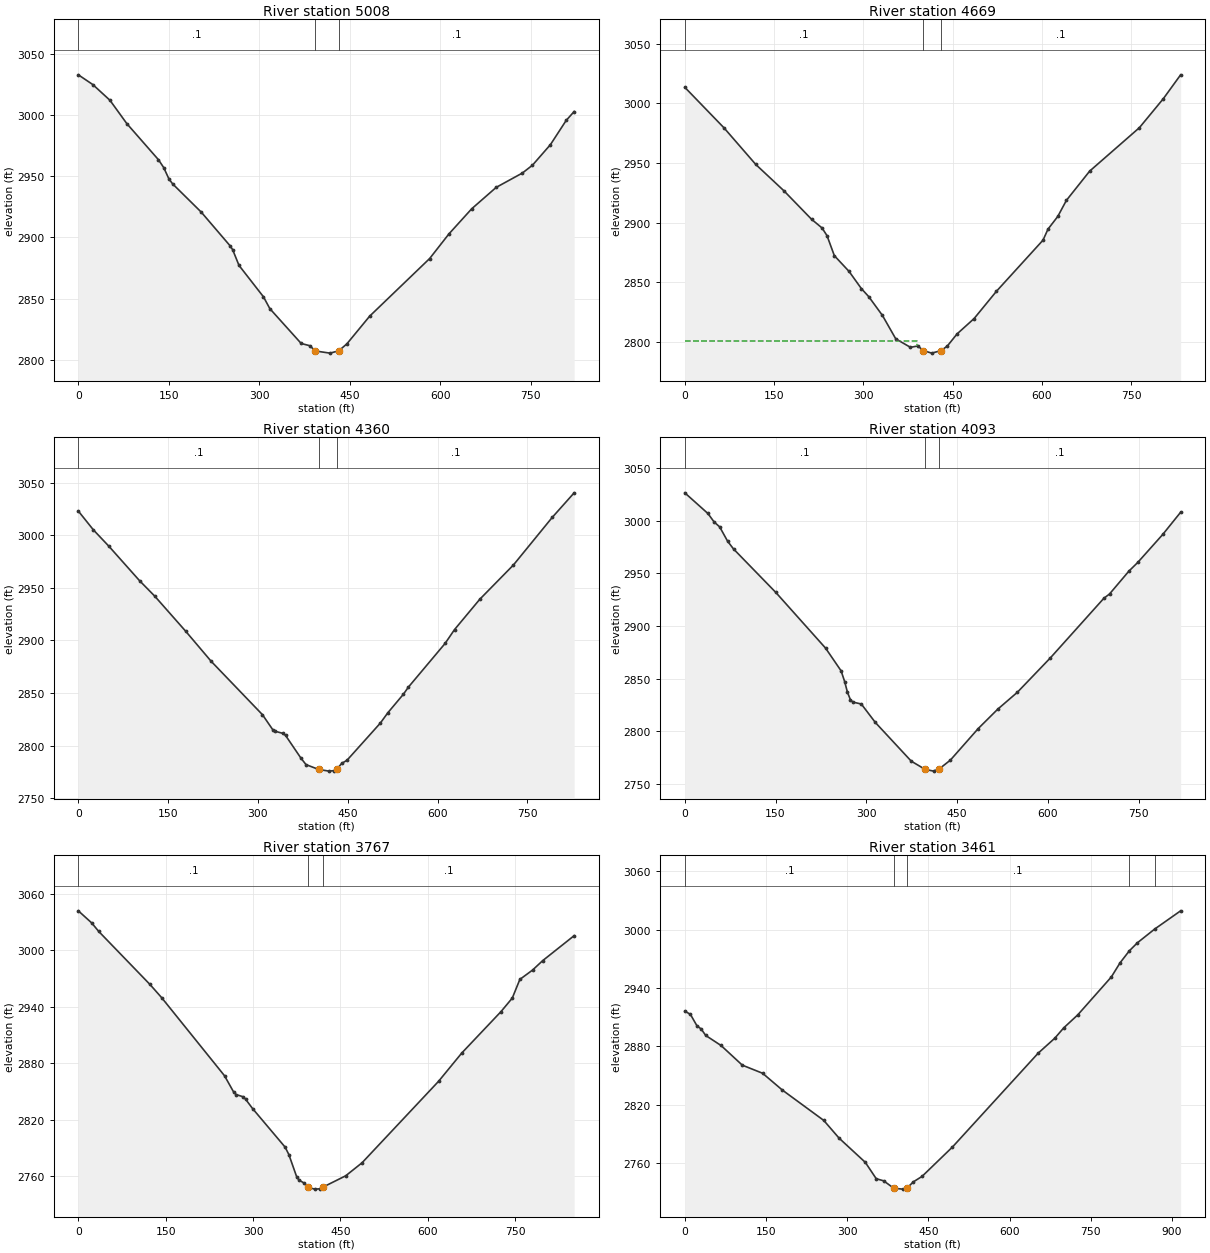
Type RM Length L Ch R = 1 ,5008    ,338.5,338.5,338.5
XS GIS Cut Line= 2
     2370033.626      580355.172     2369595.041      579660.404
#Sta/Elev= 30
       0 3032.78      24 3024.82    52.4 3011.99    80.3 2992.96   132.8 2963.41
   141.5 2956.98   150.2 2947.65   156.4 2943.62   203.7 2920.61   251.7 2892.96
   255.8 2889.85   266.2 2877.12   306.8 2851.41   317.3  2841.8   369.3 2813.31
   383.5  2811.5   392.9 2807.17     417 2805.43   431.5  2807.3     445    2813
   482.8 2835.65   582.2 2882.73   614.1 2902.82   651.8 2923.33   692.4 2940.83
   735.9 2952.58   752.5 2958.95   782.3 2975.75   808.4 2995.55   821.6  3002.8
#Mann= 3 ,-1 , 0
       0      .1       0   392.9    .045       0   431.5      .1       0
Bank Sta=392.9,431.5
XS Rating Curve= 0 ,0
Exp/Cntr=0.3,0.1

Type RM Length L Ch R = 1 ,4669    ,309.7,309.7,309.7
XS GIS Cut Line= 2
     2370193.793      580254.575     2369989.779      579446.781
#Sta/Elev= 30
       0 3013.42    65.7 2979.51   119.3  2948.7   166.5 2926.67     213 2902.76
   230.7 2895.44     239 2888.99   251.3 2872.24   276.1 2858.99   296.7 2844.63
   309.1 2837.87   332.1 2822.13   354.5  2802.5   379.2 2795.37   391.6 2796.53
   400.8 2792.67   414.8 2790.51  430.53 2792.59   441.1 2796.43   457.6 2806.65
   486.2 2819.52   523.6 2842.31     602 2885.27   610.3 2894.47   626.8 2905.14
   641.2 2918.57   680.4 2943.16   763.9 2979.54   804.2 3003.91   833.2 3023.88
#Mann= 3 ,-1 , 0
       0      .1       0   400.8    .045       0  430.53      .1       0
#XS Ineff= 2 , 0
           390.8 2800.62
Permanent Ineff=
       F       F
Bank Sta=400.8,430.53
XS Rating Curve= 0 ,0
Exp/Cntr=0.3,0.1

Type RM Length L Ch R = 1 ,4360    ,267.2,267.2,267.2
XS GIS Cut Line= 2
2370519.36044882580142.4779783472370226.47953543579368.029913389
#Sta/Elev= 30
       0 3022.98    25.2 3005.04    50.9  2989.6   102.2 2956.79   127.4 2942.19
   179.2 2908.75   221.9 2880.05   307.5 2829.31   324.6 2815.12   328.8 2813.54
   341.7 2811.54     346 2809.65   371.6 2788.11   380.2 2781.86   401.5 2777.21
   418.7 2775.65   427.2 2776.14   431.5 2777.41     440  2783.1   448.6 2785.94
   504.2 2821.24     517 2831.24   542.7 2848.68   551.2 2855.55   612.4 2897.04
   628.2 2910.24   670.4 2939.09   726.6 2971.71   791.4 3016.96     828 3040.32
#Mann= 3 ,-1 , 0
       0      .1       0   401.5    .045       0   431.5      .1       0
Bank Sta=401.5,431.5
XS Rating Curve= 0 ,0
Exp/Cntr=0.3,0.1

Type RM Length L Ch R = 1 ,4093    ,325.5,325.5,325.5
XS GIS Cut Line= 3
     2370805.482      579989.064     2370604.395      579631.979
      2370400.02      579277.065
#Sta/Elev= 30
       0 3026.26    38.2 3006.67    48.4 2998.66    57.6 2993.99    70.8 2980.33
    80.5 2973.05   150.4 2931.83   232.7 2878.97   258.3 2857.47   264.2 2847.26
   268.8 2837.17   273.8 2829.94   277.9 2827.82   291.7 2826.03   314.9 2808.52
   374.3 2771.81   397.1 2764.08   411.1 2762.39   420.6 2764.57   438.8 2772.77
     485  2802.8   517.2 2821.14   549.5 2837.09   604.2 2869.79   692.6  2926.3
   701.9 2930.34     734 2952.07   748.7 2960.34   789.9 2986.82   819.4 3007.83
#Mann= 3 ,-1 , 0
       0      .1       0   397.1    .045       0   420.6      .1       0
Bank Sta=397.1,420.6
XS Rating Curve= 0 ,0
Exp/Cntr=0.3,0.1

Type RM Length L Ch R = 1 ,3767    ,305.9,305.9,305.9
XS GIS Cut Line= 3
     2370909.495      579945.8152370897.43176771579428.202842535
     2370767.709      579120.972
#Sta/Elev= 30
       0  3041.7    22.9  3028.9    34.9 3019.93     123 2963.59     143 2949.63
     251 2866.76     267 2849.08     271 2846.83     283 2844.45   287.1  2841.9
   299.2 2831.93     355 2791.07   361.4  2783.2     375 2759.32     379 2756.08
     387 2753.15     395 2748.43   405.7 2746.53     415 2746.86     420 2748.67
     459 2760.66   487.1 2774.49   618.5 2860.93   658.3 2890.91   725.6  2934.8
     745 2949.19     758 2968.98   779.7 2978.83   797.1 2988.83   851.2 3015.37
#Mann= 3 ,-1 , 0
       0      .1       0     395    .045       0     420      .1       0
Bank Sta=395,420
XS Rating Curve= 0 ,0
Exp/Cntr=0.3,0.1

Type RM Length L Ch R = 1 ,3461    ,287.2,287.2,287.2
XS GIS Cut Line= 3
     2371242.392      579857.2072371179.47442716579400.730356309
     2370844.493      579092.829
#Sta/Elev= 30
       0 2916.16    10.4 2912.74    22.5 2900.95    30.1 2897.82    38.7 2891.05
    66.9 2880.77   106.2 2860.54   143.7  2852.2     180    2835   256.7 2803.69
     285 2785.46   333.4 2760.59   353.6 2743.74   367.3 2741.58   385.9    2734
   402.1 2733.04   410.6 2734.26   422.3 2740.58   438.2 2746.13   494.4 2776.36
   652.7 2872.87   683.4 2888.26   699.9 2898.89   725.9  2912.3   787.8 2951.23
   804.1  2965.9  821.032978.085   835.9 2986.35  867.563000.364   915.8 3019.25
#Mann= 5 ,-1 , 0
       0      .1       0   385.9    .045       0   410.6      .1       0
  821.03      .1       0  867.56      .1       0
Bank Sta=385.9,410.6
XS Rating Curve= 0 ,0
Exp/Cntr=0.3,0.1

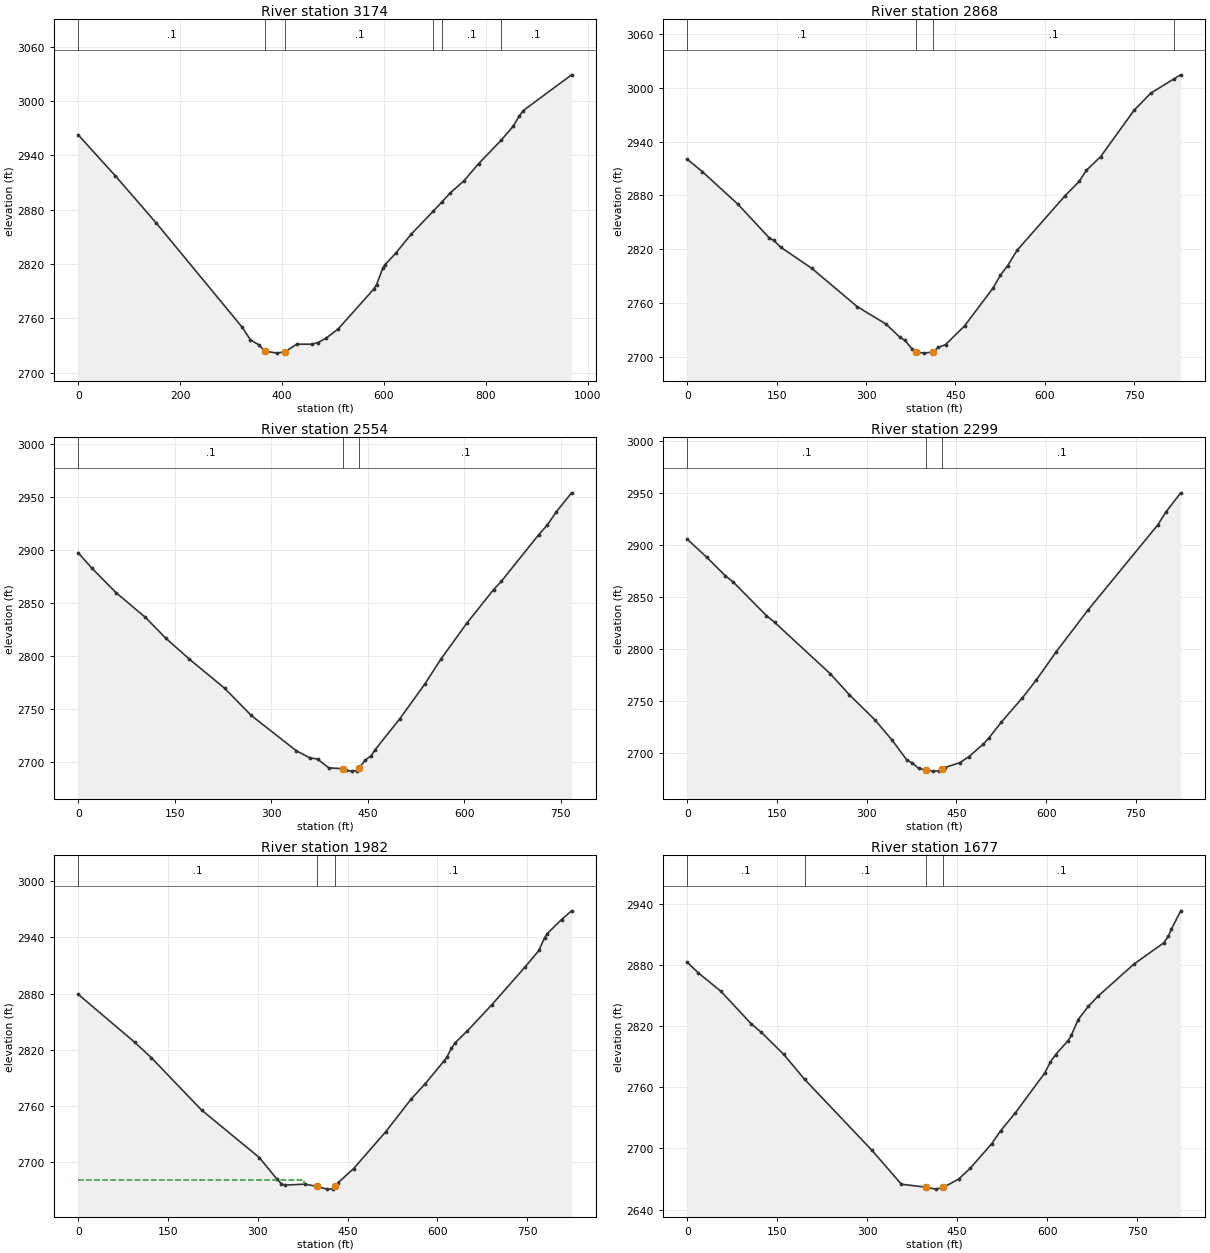
Type RM Length L Ch R = 1 ,3174    ,306.1,306.1,306.1
XS GIS Cut Line= 3
     2371767.489      579371.4622371239.74473427579329.705870083
     2370896.746      579056.441
#Sta/Elev= 30
       0 2962.67      73 2917.36   153.2 2865.33   321.7 2750.38   337.8  2736.5
   353.8 2731.15   365.9 2724.04     390 2721.78   406.5 2723.56   428.8 2731.67
   458.2 2731.63   470.2 2733.41   486.3 2738.25     510 2748.44   580.5 2792.93
   585.3  2797.4   597.6 2815.52   602.3 2819.56   623.2  2832.2   653.4 2853.15
  696.782878.609  713.512888.592   730.1 2898.71     757 2912.09   785.4 2930.83
  829.322956.478   853.8 2972.46   865.1 2983.49   873.3 2989.54   967.9 3028.94
#Mann= 6 ,-1 , 0
       0      .1       0   365.9    .045       0   406.5      .1       0
  696.78      .1       0  713.51      .1       0  829.32      .1       0
Bank Sta=365.9,406.5
XS Rating Curve= 0 ,0
Exp/Cntr=0.3,0.1

Type RM Length L Ch R = 1 ,2868    ,313.8,313.8,313.8
XS GIS Cut Line= 2
     2371779.474      579061.1922370952.48219488579019.336173223
#Sta/Elev= 30
       0 2920.11    24.8 2906.56    84.8 2870.11   136.9 2832.93   144.9 2829.68
   156.9 2822.03     209  2798.5   285.2 2755.82   333.2 2736.53   357.2 2721.49
   365.4 2718.27   377.2 2708.41   384.1 2705.36   397.2 2704.04   411.8 2705.37
   421.3 2710.51   433.3 2713.56   465.3 2734.45   513.4 2777.01   525.4 2790.94
   537.4 2801.43   553.4 2818.77   633.5 2879.25   657.6  2895.5   669.6 2907.87
   693.6 2923.14   749.7 2974.81   777.7 2993.88  817.033010.063   828.1  3014.4
#Mann= 4 ,-1 , 0
       0      .1       0   384.1    .045       0   411.8      .1       0
  817.03      .1       0
Bank Sta=384.1,411.8
XS Rating Curve= 0 ,0
Exp/Cntr=0.3,0.1

Type RM Length L Ch R = 1 ,2554    ,255.1,255.1,255.1
XS GIS Cut Line= 3
2371678.61372441 578602.884746062371404.98378091578693.368107297
2370977.31202755578907.904043306
#Sta/Elev= 30
       0  2897.4    20.9 2883.08    58.8 2859.82   104.4  2836.6     136 2817.03
   172.6 2797.35   227.4 2769.94     269 2744.22   338.7 2711.15   359.5  2704.5
   371.9 2703.19   389.3 2694.96   411.5 2694.17   416.2  2692.6   425.4 2691.87
   433.9 2692.38     437 2695.16     446 2702.28   454.9 2706.03   461.1 2711.76
   499.6 2741.02   538.4 2773.61   563.7 2797.36   603.8 2830.95   645.6 2862.79
   657.6 2870.52   715.8 2914.47   729.3  2923.7   742.7 2935.62   766.7 2953.77
#Mann= 3 ,-1 , 0
       0      .1       0   411.5    .045       0     437      .1       0
Bank Sta=411.5,437
XS Rating Curve= 0 ,0
Exp/Cntr=0.3,0.1

Type RM Length L Ch R = 1 ,2299    ,316.9,316.9,316.9
XS GIS Cut Line= 2
 2371513.3937494578293.324368892     2370842.283      578773.369
#Sta/Elev= 30
       0 2905.76    32.8 2888.34    63.2 2870.82      77 2864.49     132 2832.44
   145.9 2825.88   239.3 2776.22   270.8 2756.24   313.1 2732.32   342.6 2712.35
   367.1 2693.29   375.7 2690.74   386.9 2685.21   398.7 2683.82   411.4 2682.67
   421.6 2683.02   426.2 2684.47   430.2 2686.05   455.7 2690.86   470.4  2696.4
   495.1 2708.87   504.8 2714.99   524.8 2729.67   559.6 2752.78   583.6 2770.46
   616.6 2797.41   669.6 2837.46   786.5 2919.58   800.2 2932.04   825.1 2950.56
#Mann= 3 ,-1 , 0
       0      .1       0   398.7    .045       0   426.2      .1       0
Bank Sta=398.7,426.2
XS Rating Curve= 0 ,0
Exp/Cntr=0.3,0.1

Type RM Length L Ch R = 1 ,1982    ,305.4,305.4,305.4
XS GIS Cut Line= 2
      2371347.64       578068.75     2370639.976      578491.433
#Sta/Elev= 30
       0 2879.26    94.2  2828.1   122.2 2811.52     206 2755.66   302.7 2704.74
   331.8 2681.96   339.6  2676.8   345.8 2675.36   378.5  2676.4   398.9 2673.98
   415.7 2671.06     425 2671.47   429.7  2674.3   434.3    2678   460.2 2693.04
   513.6 2732.22   556.4 2767.38   579.8  2783.7   611.4 2808.13   616.1 2812.33
   623.5 2821.38     630 2827.54   649.8 2839.92   690.6 2867.76   746.5 2908.34
   769.8 2926.16   779.1 2939.58   783.8 2944.23   807.6 2959.18   824.3 2968.46
#Mann= 3 ,-1 , 0
       0      .1       0   398.9    .045       0   429.7      .1       0
#XS Ineff= 2 , 0
          376.64 2681.24
Permanent Ineff=
       F       F
Bank Sta=398.9,429.7
XS Rating Curve= 0 ,0
Exp/Cntr=0.3,0.1

Type RM Length L Ch R = 1 ,1677    ,300.6,300.6,300.6
XS GIS Cut Line= 2
      2371275.88      577875.638     2370491.743      578125.165
#Sta/Elev= 30
       0 2882.38      18 2872.28    55.8 2854.12   106.1 2822.41   122.9 2814.09
   160.7 2792.18  195.69 2767.63   307.6 2698.24     357 2664.84   398.4 2661.94
   414.3 2660.04     427 2661.81   452.5 2669.92   471.6 2680.42   507.8 2704.77
   522.5 2717.37   546.9 2734.77   595.8 2773.72   605.3 2784.57     614 2791.95
     635 2805.73   640.4 2810.92   651.8  2826.4   668.6 2839.26   684.9 2849.28
   744.2  2880.5   794.5 2901.61   802.2 2907.94   807.1 2914.89   822.9 2933.03
#Mann= 4 ,-1 , 0
       0      .1       0  195.69      .1       0   398.4    .045       0
     427      .1       0
Bank Sta=398.4,427
XS Rating Curve= 0 ,0
Exp/Cntr=0.3,0.1

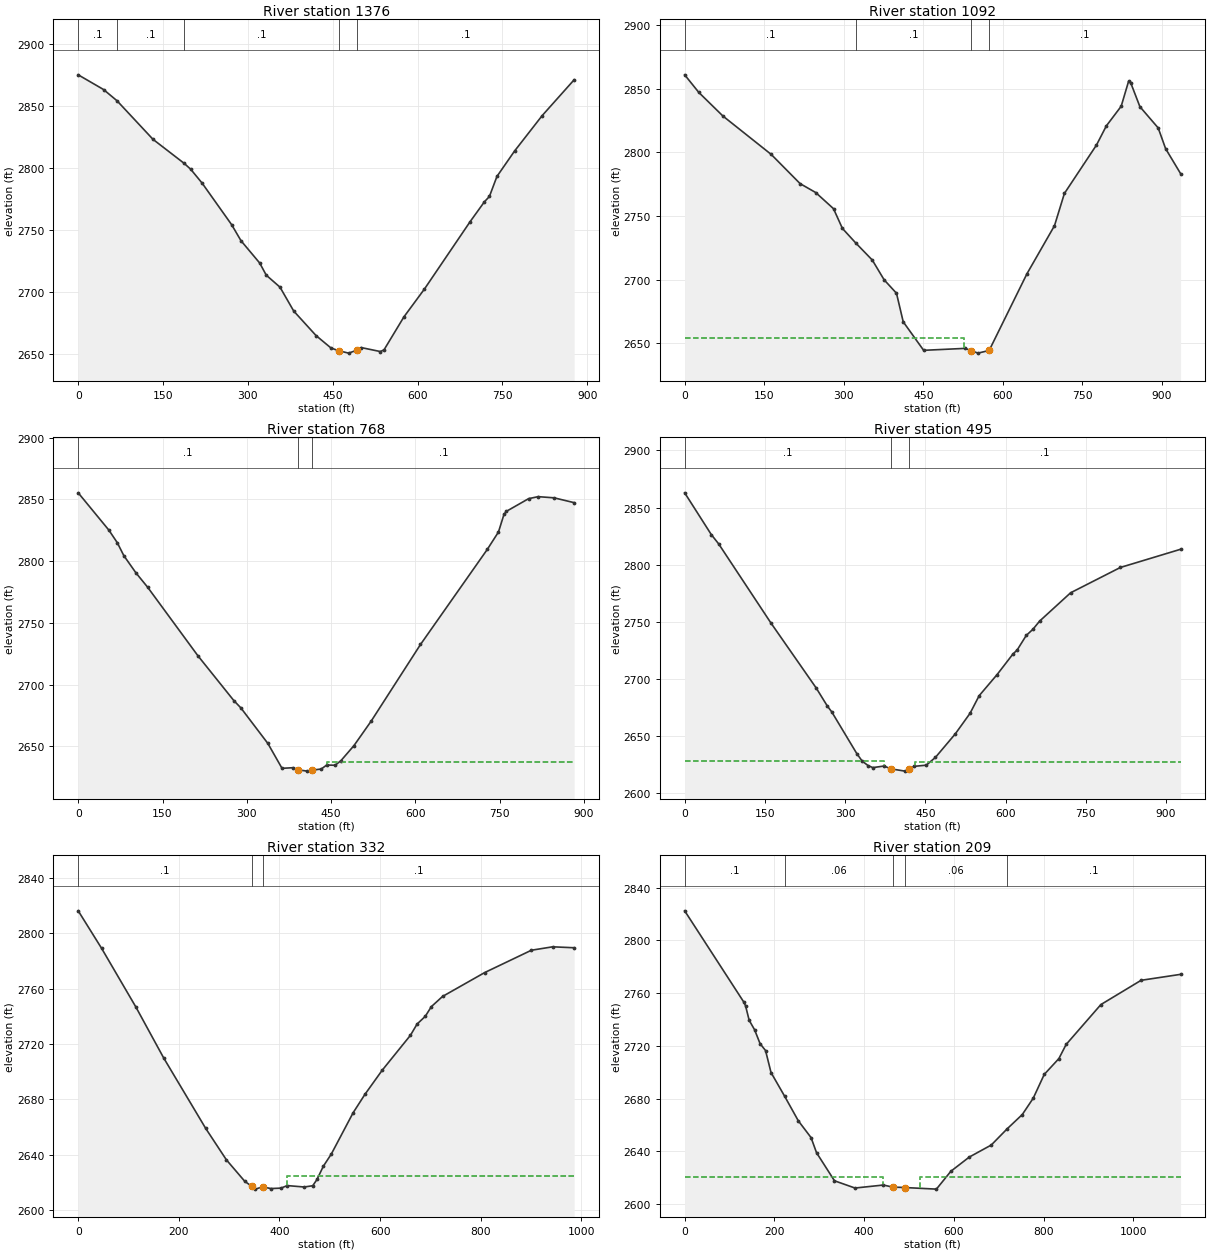
Type RM Length L Ch R = 1 ,1376    ,284.3,284.3,284.3
XS GIS Cut Line= 3
     2371238.998      577745.9862370855.35932479577684.917761819
2370415.87321063577897.652080717
#Sta/Elev= 30
       0 2875.11    44.8 2863.25   68.532854.226   132.2  2823.1  187.352803.707
   198.9 2798.96     219 2787.81   271.2 2754.28   287.8 2741.33   320.9 2723.32
   332.4 2713.57   356.7  2703.9     381 2684.62   420.5 2664.84   446.9 2654.83
   460.3 2652.68     478 2650.71   492.2    2653   500.3 2655.19   534.1 2651.98
   540.6 2653.36   575.8 2679.96     612 2702.36   692.8 2756.72     718 2772.69
   726.9 2777.03   740.2 2793.17   771.3 2813.63   820.2 2842.25   876.7 2871.13
#Mann= 5 ,-1 , 0
       0      .1       0   68.53      .1       0  187.35      .1       0
   460.3    .045       0   492.2      .1       0
Bank Sta=460.3,492.2
XS Rating Curve= 0 ,0
Exp/Cntr=0.3,0.1

Type RM Length L Ch R = 1 ,1092    ,323.6,323.6,323.6
XS GIS Cut Line= 3
     2371238.332      577672.6842370910.67354089577568.959608477
      2370402.47      577265.978
#Sta/Elev= 30
       0 2861.02    26.6  2847.2    72.2 2828.58   163.2 2798.41   217.7 2775.43
   247.1 2768.43   280.7 2755.71   297.5 2740.19  322.852728.649   353.9 2715.28
   376.2 2699.75   399.5 2689.18   412.2 2666.72   450.7 2644.28   528.9 2645.82
   540.6 2644.04   553.2 2642.08   574.3 2644.18   645.6 2704.53   697.5 2742.32
   716.2 2767.71   776.7 2805.78   795.3 2820.84   823.3 2836.29   837.2 2855.84
   841.1 2854.93   858.6 2835.96   893.1 2819.24   907.1 2802.93   935.4 2783.27
#Mann= 4 ,-1 , 0
       0      .1       0  322.85      .1       0   540.6    .045       0
   574.3      .1       0
#XS Ineff= 2 , 0
          527.56 2653.86
Permanent Ineff=
       F       F
Bank Sta=540.6,574.3
XS Rating Curve= 0 ,0
Exp/Cntr=0.3,0.1

Type RM Length L Ch R = 1 ,768     ,272.6,272.6,272.6
XS GIS Cut Line= 2
     2371291.108       577627.72 2370678.0824873576993.098322536
#Sta/Elev= 30
       0 2855.29    54.6 2825.07    69.6 2814.86    81.1 2804.48   102.7  2790.5
   123.5 2778.88     213 2723.35   276.9 2687.08   289.4 2681.17   337.5 2652.34
   362.6 2632.25   382.7 2632.75   390.5 2631.11   407.1 2629.97   416.7 2630.83
   432.3 2631.65   442.1 2634.89   457.2 2634.73   467.6 2638.52   490.6 2650.62
   521.4 2670.56     609  2732.5   727.9 2809.52   747.7 2823.54   757.5 2837.75
   761.8  2840.3   801.4 2850.58   818.4 2852.19   846.7 2851.24   882.4 2847.33
#Mann= 3 ,-1 , 0
       0      .1       0   390.5    .045       0   416.7      .1       0
#XS Ineff= 2 , 0
                          442.78         2637.43
Permanent Ineff=
       F       F
Bank Sta=390.5,416.7
XS Rating Curve= 0 ,0
Exp/Cntr=0.3,0.1

Type RM Length L Ch R = 1 ,495     ,163.4,163.4,163.4
XS GIS Cut Line= 3
2371466.44109279577489.1081296822371139.03104422577067.732865372
2370763.17018128576950.276345703
#Sta/Elev= 30
       0 2862.95    49.8 2826.39    63.6 2818.23     161 2749.22     246 2692.09
   266.8  2676.3     275 2671.23   321.9 2634.68     332  2628.1   343.4 2624.06
     352 2622.45   372.6  2623.8   386.2 2621.32   411.9 2619.36   420.4 2620.95
     429 2623.54   451.8 2624.58   468.9 2631.37   505.9 2651.88   533.6 2669.93
   550.7  2685.4   584.2 2703.85   613.5 2721.66   621.9 2725.49   638.7  2738.1
   651.3 2743.56   663.8  2750.7   721.7 2775.46   814.7 2797.61927.4099 2813.55
#Mann= 3 ,-1 , 0
       0      .1       0   386.2    .045       0   420.4      .1       0
#XS Ineff= 2 , 0
          372.47 2628.23  431.47         2627.76
Permanent Ineff=
       F       F
Bank Sta=386.2,420.4
XS Rating Curve= 0 ,0
Exp/Cntr(USF)=0,0
Exp/Cntr=0.3,0.1

Type RM Length L Ch R = 1 ,332     ,123.2,123.2,123.2
XS GIS Cut Line= 3
2371528.10576562 577330.541828132371445.88620185577105.906234264
2370738.21067085576868.056781935
#Sta/Elev= 30
       0  2816.1    46.5 2789.04   114.6 2746.72     170  2709.9   253.5 2659.09
   294.6 2636.45   331.1 2620.96  345.45 2617.24   352.2 2615.34   366.5 2617.02
     383 2615.75   402.9 2616.06   415.5 2617.89   449.3 2616.88   466.2  2617.8
   474.6 2622.29   487.3 2631.89   503.1 2640.66   546.4  2670.4   569.9  2683.7
   604.1 2701.04   660.3 2726.28   673.6 2734.43   689.8 2739.97     702    2747
   724.1 2754.31     808 2771.57   900.8 2787.67     943 2790.14985.7864 2789.46
#Mann= 3 ,-1 , 0
       0      .1       0  345.45    .045       0   366.5      .1       0
#XS Ineff= 2 , 0
                          414.21         2624.83
Permanent Ineff=
       F       F
Bank Sta=345.45,366.5
XS Rating Curve= 0 ,0
Exp/Cntr(USF)=0,0
Exp/Cntr=0.3,0.1

Type RM Length L Ch R = 1 ,209     ,155.9,155.9,155.9
XS GIS Cut Line= 3
2371557.68276207577308.5636379072371501.79548181576979.506261642
2370744.29636337576834.332939745
#Sta/Elev= 30
       0 2822.33   131.5 2753.28   135.6 2750.38   143.7 2739.37   155.9 2732.08
     168 2721.63   180.2 2716.42   192.4 2699.75  222.952681.652   253.2 2663.16
   281.6 2650.43   293.8 2638.98   333.8 2617.69   379.5  2612.2   442.8 2614.47
   463.1 2612.94   491.6 2612.56   560.9 2611.37   593.2 2624.93   634.2 2635.69
   683.1 2644.79   718.52657.067   752.3 2667.92   776.7 2680.33   801.2 2698.33
   833.8 2710.33     850 2721.05   927.4 2751.27    1017 2769.661105.054 2774.18
#Mann= 5 ,-1 , 0
       0      .1       0  222.95     .06       0   463.1    .045       0
   491.6     .06       0   718.5      .1       0
#XS Ineff= 2 , 0
          442.27 2620.75  525.35         2620.21
Permanent Ineff=
       F       F
Bank Sta=463.1,491.6
XS Rating Curve= 0 ,0
Exp/Cntr(USF)=0,0
Exp/Cntr=0.3,0.1

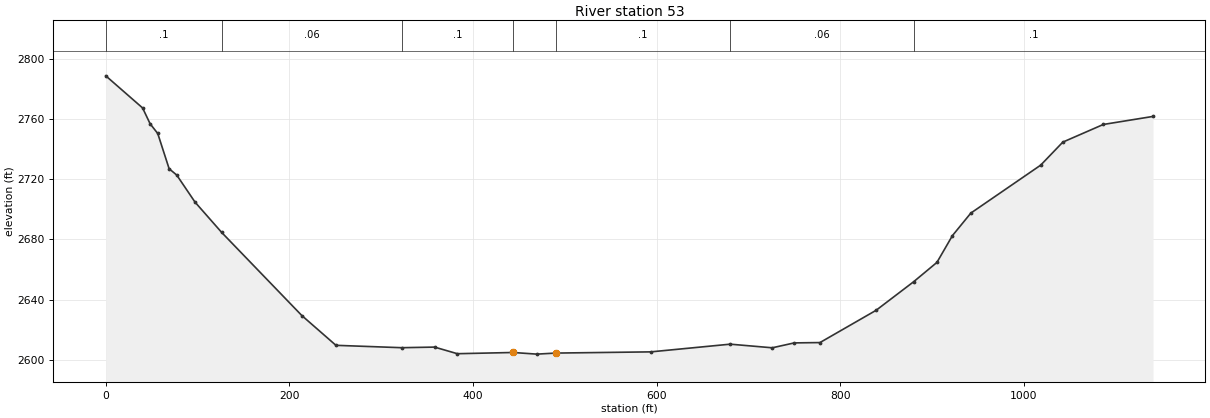
Type RM Length L Ch R = 1 ,53      ,,,
XS GIS Cut Line= 4
2371586.33009294577205.7129444552371489.86892616576830.642461119
 2371296.7434956576777.3326026762370744.60730886576809.297190574
#Sta/Elev= 30
       0 2788.74    40.1 2767.39    48.3 2756.87    56.6 2750.42      69    2727
    77.3 2722.79    97.2 2704.83  126.29 2684.64   213.6 2629.42   250.7 2609.67
  322.282608.092   358.1 2608.49   382.9  2604.1   443.7 2604.91   469.4 2603.82
   490.4 2604.52   593.6 2605.32  680.142610.434   725.9 2608.03   749.9 2611.28
   777.9  2611.5     839 2632.93  879.832651.874   905.3 2664.78   922.2 2682.59
   942.2 2697.52  1018.3 2729.39  1042.4 2744.69  1086.5 2756.421140.685 2761.77
#Mann= 7 ,-1 , 0
       0      .1       0  126.29     .06       0  322.28      .1       0
   443.7    .045       0   490.4      .1       0  680.14     .06       0
  879.83      .1       0
Bank Sta=443.7,490.4
XS Rating Curve= 0 ,0
Exp/Cntr(USF)=0,0
Exp/Cntr=0.3,0.1
LCMann Table=0

Chan Stop Cuts=-1
Use User Specified Reach Order=0
Composite Channel Slope=5